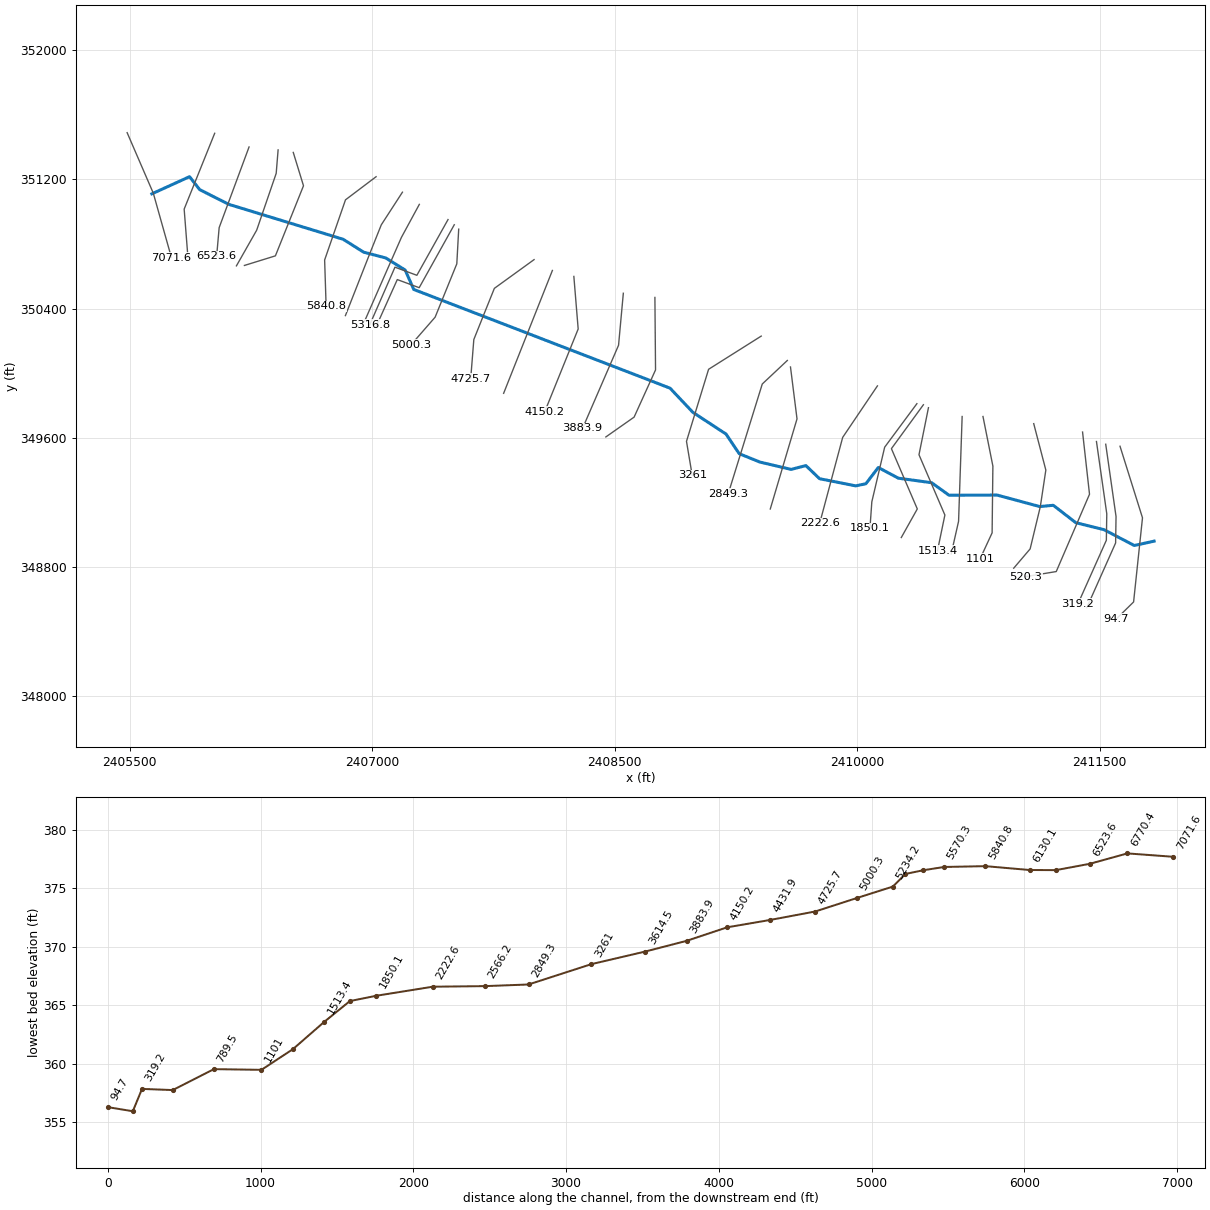
--- TUSCARORA3.prj (project) ---

Proj Title=TUSCARORA3
Current Plan=p01
Default Exp/Contr=0,0
English Units
Geom File=g01
Flow File=f01
Plan File=p01
BEGIN DESCRIPTION:
END DESCRIPTION:
DSS Export Rating Curves= 0
DSS Export Rating Curve Sorted= 0
DSS Export Volume Flow Curves= 0
DXF OffsetX= 0
DXF OffsetY= 0
DXF ScaleX= 0
DXF ScaleY= 0

--- TUSCARORA3.p01 (plan) ---

Plan Title=Floodplain
Program Version=4.00
Geom File=g01
Flow File=f01
K Sum by GR=0
Std Step Tol=0.01
Critical Tol=0.01
Num of Std Step Trials=20
Max Error Tol=0.3
Flow Tol Ratio=0.001
Split Flow NTrial=30
Split Flow Tol=0.02
Split Flow Ratio=0.02
Log Output Level=0
Friction Slope Method=1
Unsteady Friction Slope Method=2
Unsteady Bridges Friction Slope Method=1
Global Log Level=0
CheckData=False
Run HTab=0
Run UNet=0
Run PostProcess=0
UNET Theta=0
UNET Theta Warmup=0
UNET ZTol=0
UNET ZSATol=0
UNET MxIter=0
UNET MaxInSteps=0
UNET DtIC=0
UNET DtMin=0
UNET MaxCRTS=0
UNET WFStab=0
UNET SFStab=0
UNET WFX=0
UNET SFX=0
UNET DSS MLevel=0
UNET DZMax Abort=0
UNET Convert EG Bridges=0
UNET Use Existing IB Tables=0
UNET Froude Limit=0
UNET Froude Power=0
Write IC File=0
Echo Input=False
Echo Output=False
Write Detailed=0

--- TUSCARORA3.f01 (steady flow) ---

Flow Title=NFF Regression Equation
Program Version=5.03
Number of Profiles= 1
Profile Names=P100yr
River Rch & RM=TUSCARORA3,Main            ,7071.6
    2000
Boundary for River Rch & Prof#=TUSCARORA3,Main            , 1
Up Type= 0
Dn Type= 3
Dn Slope=0.00553
Set Internal Change=TUSCARORA3      ,Main            ,6302.2  , 1 , 3 ,384
DSS Import GetInterval= 0
DSS Import GetPeak= 0
DSS Import FillOption= 0

--- TUSCARORA3.g01 (geometry) ---

Geom Title=USGS 10m DEM
Program Version=5.03

River Reach=TUSCARORA3      ,Main
Reach XY= 30
     2405637.044       351110.87     2405870.333      351217.207
     2405933.267      351136.912     2406113.389      351045.766
     2406820.831      350829.196     2406946.722      350749.542
     2407083.441      350713.735     2407203.884      350638.865
     2407257.052      350518.422     2408842.339      349906.443
     2408983.398      349756.703     2409188.476      349622.155
     2409269.856      349500.627     2409397.894      349448.544
     2409591.037      349402.971     2409682.182      349426.842
     2409766.818      349345.462     2409990.342      349300.974
     2410053.276      349313.995     2410130.316      349414.906
     2410254.014      349348.717     2410460.003      349320.592
     2410567.816      349242.988     2410865.212       349244.03
      2411128.45      349172.806     2411212.651      349180.619
      2411351.54       349072.98     2411526.019      349029.577
     2411713.519      348931.486     2411835.915      348958.396

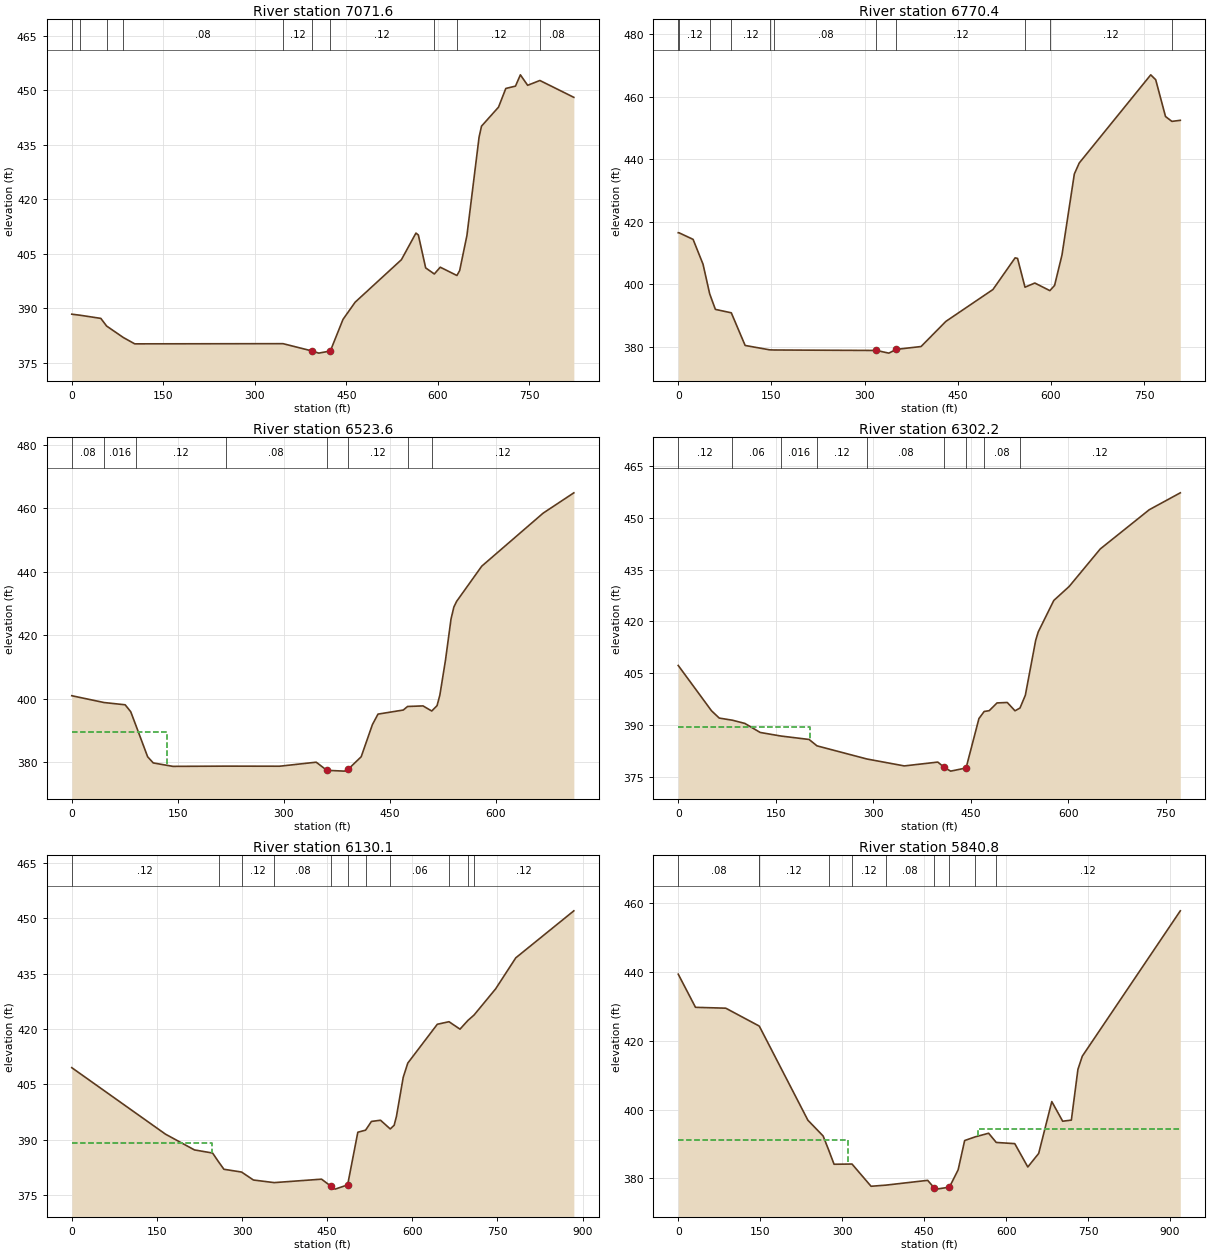
Type RM Length L Ch R = 1 ,7071.6  ,317.6,301.2,286.7
XS GIS Cut Line= 3
     2405484.339      351490.116     2405646.226      351114.831
     2405758.164      350716.293
#Sta/Elev= 30
       0  388.41   13.09388.1405    47.6  387.26    57.1385.1585   84.55 381.995
   103.2  380.26  346.19380.3104   393.7 378.302   404.7  377.71   423.7 378.295
   444.5     387   464.4  391.72   540.1  403.38     564  410.71   567.9  410.18
   579.9  401.14  594.09399.4691   603.8  401.33  631.09399.0502   635.6   400.4
   647.5  410.05   667.4  437.06   671.4   440.1   699.3  445.33   711.2  450.46
   727.1  451.11   735.1  454.21     747  451.33  767.04452.6557   822.7  448.02
#Mann= 10 ,-1 , 0
       0     .12       0   13.09    .016       0    57.1     .12       0
   84.55     .08       0  346.19     .12       0   393.7    .045       0
   423.7     .12       0  594.09     .08       0  631.09     .12       0
  767.04     .08       0
Bank Sta=393.7,423.7
XS Rating Curve= 0 ,0
Exp/Cntr=0.3,0.1

Type RM Length L Ch R = 1 ,6770.4  ,249.3,246.8,244.3
XS GIS Cut Line= 3
     2406025.835      351486.307     2405837.033      351016.255
     2405860.471      350715.474
#Sta/Elev= 30
       0  416.48     1.4416.4485    23.9  414.36    39.9  406.43   50.63 396.944
    59.8  391.98   85.42390.8838   107.7  380.45  147.41 379.041   154.9379.0035
   319.1  378.85     339     378     351   379.2   390.9  380.11   430.8  388.14
   506.6  398.33   542.3  408.45   546.2  408.27   558.2  399.07     574   400.4
  598.23397.9711   605.8  399.64   617.7  409.33   637.6  435.24   645.5  438.76
   760.6  466.94   768.6  465.37   784.4  453.62  794.61452.0607   808.2   452.4
#Mann= 11 ,-1 , 0
       0     .08       0     1.4     .12       0   50.63    .016       0
   85.42     .12       0  147.41     .06       0   154.9     .08       0
   319.1    .045       0     351     .12       0   558.2     .08       0
  598.23     .12       0  794.61     .08       0
Bank Sta=319.1,351
XS Rating Curve= 0 ,0
Exp/Cntr=0.3,0.1

Type RM Length L Ch R = 1 ,6523.6  ,220.8,221.4,221.9
XS GIS Cut Line= 3
     2406238.401      351401.518     2406053.505      350901.518
      2406037.88      350724.434
#Sta/Elev= 30
       0  400.88   45.57398.7383    75.6  398.02    83.5  395.83    90.9 391.468
   107.4  381.65   115.4  379.69   143.2  378.61  217.76378.6822   294.4  378.66
   346.1  379.93   361.2  377.36   385.9  377.11   391.2377.6633   409.8  381.64
   425.7  391.79   433.6  395.08   469.4  396.37  475.45  397.49   497.3  397.67
  509.71396.0604   517.2  397.75   521.2  401.09   529.1  412.01     537  425.06
     541  428.82   544.9  430.62   580.5  441.72   667.4  458.43   710.9  464.84
#Mann= 8 ,-1 , 0
       0     .08       0   45.57    .016       0    90.9     .12       0
  217.76     .08       0   361.2    .045       0   391.2     .12       0
  475.45     .08       0  509.71     .12       0
#XS Ineff= 2 , 0
           135.4  389.39
Permanent Ineff=
       F       F
Bank Sta=361.2,391.2
XS Rating Curve= 0 ,0
Exp/Cntr=0.3,0.1

Type RM Length L Ch R = 1 ,6302.2  ,173.3,172.1,171
XS GIS Cut Line= 4
     2406418.088      351383.288     2406406.262      351237.919
     2406285.601      350885.781     2406160.276      350664.538
#Sta/Elev= 30
       0   407.2    51.2  394.06    63.1  391.95   83.44 391.327   102.5   390.4
   126.1  387.78  157.97386.7433   201.3  385.75  213.48 383.897  290.26380.0867
   347.8  378.08   399.3  379.19   409.4  377.63   419.1  376.57   442.8  377.48
   462.6   391.8  470.65393.8611   478.5   394.1   490.4  396.34   506.2  396.47
   518.1  394.06  525.75394.8662     534  398.57   549.9  414.48   553.8  416.91
   577.7  426.03   601.5  430.12   649.2  440.97   724.7  452.36   772.4  457.25
#Mann= 9 ,-1 , 0
       0     .12       0   83.44     .06       0  157.97    .016       0
  213.48     .12       0  290.26     .08       0   409.4    .045       0
   442.8     .12       0  470.65     .08       0  525.75     .12       0
#XS Ineff= 2 , 0
          202.27  389.39
Permanent Ineff=
       F       F
Bank Sta=409.4,442.8
XS Rating Curve= 0 ,0
Exp/Cntr=0.3,0.1

Type RM Length L Ch R = 1 ,6130.1  ,288.3,289.3,290
XS GIS Cut Line= 4
     2406511.838      351367.663     2406575.098      351161.003
     2406401.337      350726.601     2406209.755      350667.143
#Sta/Elev= 30
       0   409.5     165  391.49   216.1  387.21   248.1  386.36  258.55384.0056
   268.1  381.96  299.11381.2109   320.1  379.05  356.66378.3442   440.1  379.28
   456.1  377.43     464  376.58  486.04377.7323     504     392  517.67392.5634
     528  394.93     544  395.25  561.13392.8911     568  393.89     572  396.27
     584   406.9     592  410.73     644  421.26  664.65421.9568     684  419.94
  697.83422.2807  708.84423.7794   746.9  430.88   782.3  439.27   884.6  452.01
#Mann= 11 ,-1 , 0
       0     .12       0  258.55    .016       0  299.11     .12       0
  356.66     .08       0   456.1    .045       0  486.04     .12       0
  517.67     .08       0  561.13     .06       0  664.65     .12       0
  697.83     .06       0  708.84     .12       0
#XS Ineff= 2 , 0
          247.68  389.05
Permanent Ineff=
       F       F
Bank Sta=456.1,486.04
XS Rating Curve= 0 ,0
Exp/Cntr=0.3,0.1

Type RM Length L Ch R = 1 ,5840.8  ,272.2,270.4,266.6
XS GIS Cut Line= 4
     2407024.099      351217.065     2406834.863      351073.836
     2406705.855      350701.025     2406715.072      350414.114
#Sta/Elev= 30
       0  439.33    31.6   429.7      87  429.45  147.23424.3457  148.59424.1748
   237.3  396.92   265.2  392.34  275.17388.3359   285.2  384.13  318.04384.1972
   352.9  377.74  380.19378.0719   456.5  379.46   468.4  377.29   472.4  376.91
   496.3  377.48   512.3  382.52   524.2  391.02  543.63392.0933   568.1  393.14
  582.07390.4634   615.9  390.12   639.8  383.34   659.7  387.28   683.7  402.33
   703.6  396.63   719.5  396.95   731.5  411.67   739.5  415.51   918.9  457.72
#Mann= 10 ,-1 , 0
       0     .08       0  147.23     .06       0  148.59     .12       0
  275.17    .016       0  318.04     .12       0  380.19     .08       0
   468.4    .045       0   496.3     .12       0  543.63     .08       0
  582.07     .12       0
#XS Ineff= 2 , 0
          311.46  391.05  549.02          394.46
Permanent Ineff=
       F       F
Bank Sta=468.4,496.3
XS Rating Curve= 0 ,0
Exp/Cntr=0.3,0.1

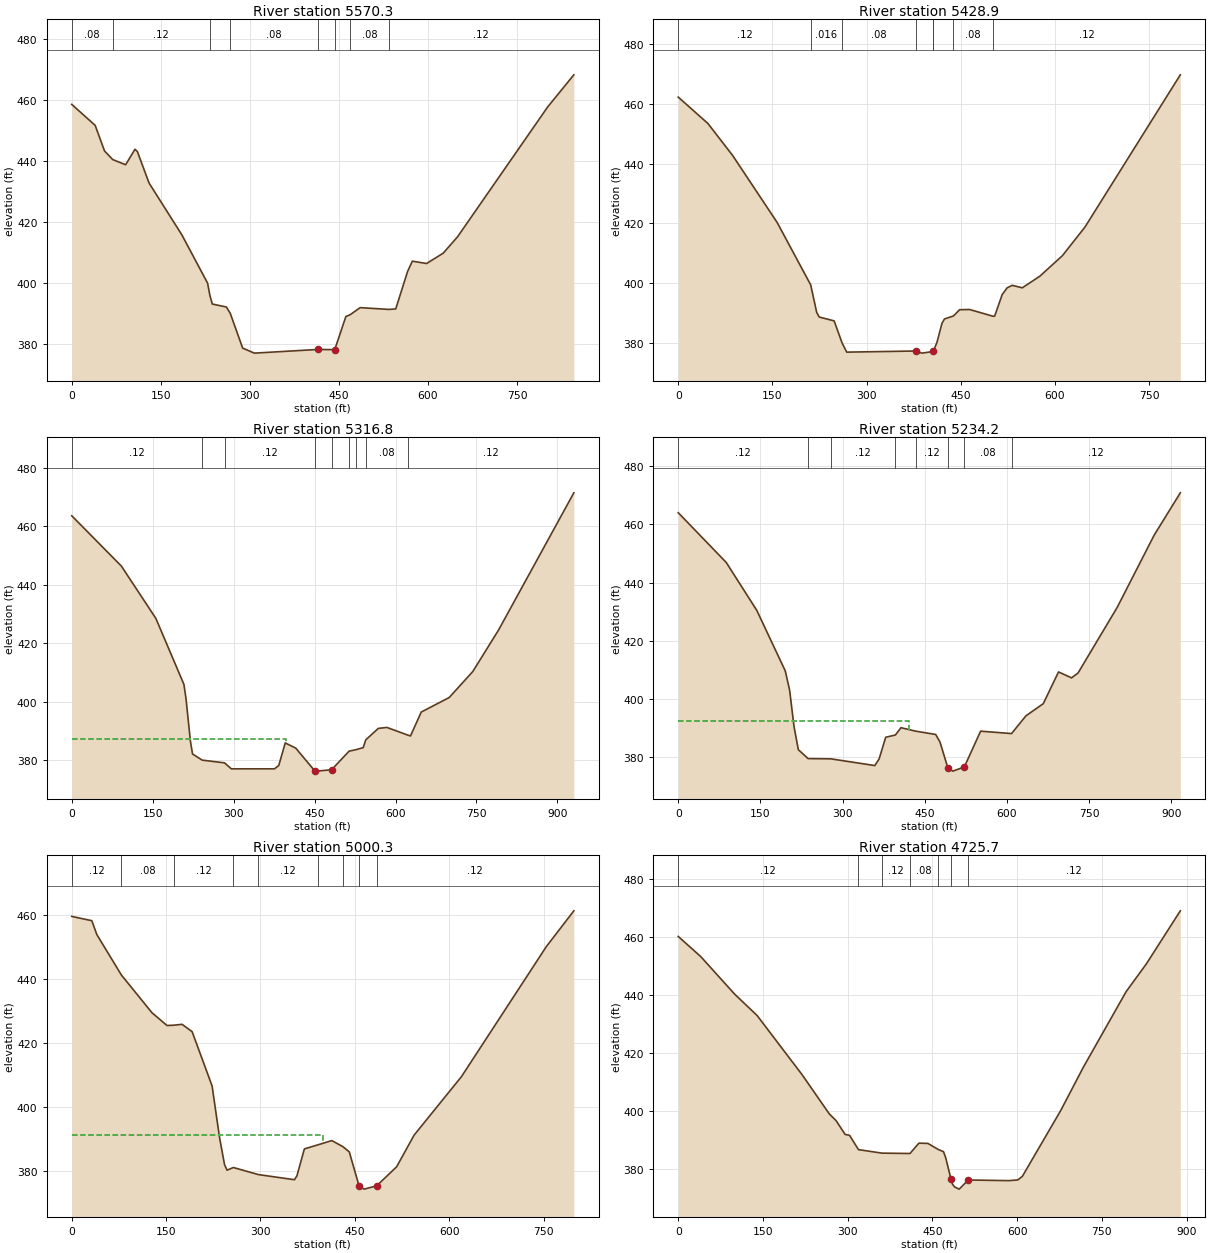
Type RM Length L Ch R = 1 ,5570.3  ,142.2,141.5,140.5
XS GIS Cut Line= 4
     2407187.077      351121.145     2407056.372      350919.087
     2406984.822      350739.796     2406834.354      350356.276
#Sta/Elev= 30
       0  458.65    39.4  451.76    55.2  443.33   68.93 440.516    90.7   438.8
   106.5   443.9   110.5  443.15   130.2  432.79   185.4  415.76   228.8  399.85
  232.58395.8904   236.7  392.99   260.4  392.01  266.91389.9589   287.9  378.48
   307.6  376.84     414  378.04  442.96377.9884   461.7  388.88  468.81389.4578
   485.7   391.8  534.06391.2173   545.7  391.38   565.7  403.72   573.7  407.09
   597.7  406.32   625.7  409.73   649.7  415.07   801.7  457.83   845.7  468.38
#Mann= 8 ,-1 , 0
       0     .08       0   68.93     .12       0  232.58    .016       0
  266.91     .08       0     414    .045       0  442.96     .12       0
  468.81     .08       0  534.06     .12       0
Bank Sta=414,442.96
XS Rating Curve= 0 ,0
Exp/Cntr=0.3,0.1

Type RM Length L Ch R = 1 ,5428.9  ,152,112.1,37.9
XS GIS Cut Line= 3
     2407291.569      351045.678     2407180.892      350841.251
     2406953.027       350321.72
#Sta/Elev= 30
       0  462.25    47.3  453.41    86.7   442.7   157.6  420.28     211 399.401
   220.6  390.16   224.6  388.63   248.4  387.34  260.94380.0032   268.4  376.88
     378377.2565   388.3  376.55  405.99377.1017  406.28377.1684   412.2  380.18
   420.2  386.58   424.2     388  438.28388.9628   448.2  391.08   464.2  391.15
  501.57388.8841   504.1  388.96   516.1  396.17   524.1  398.43   532.1  399.25
   548.1  398.41     576  402.29     612  409.18     648  418.77   799.8   469.7
#Mann= 8 ,-1 , 0
       0     .12       0     211    .016       0  260.94     .08       0
     378    .045       0  405.99     .08       0  406.28     .12       0
  438.28     .08       0  501.57     .12       0
Bank Sta=378,405.99
XS Rating Curve= 0 ,0
Exp/Cntr=0.3,0.1

Type RM Length L Ch R = 1 ,5316.8  ,102.9,82.6,122.1
XS GIS Cut Line= 4
     2407469.032      350951.549     2407276.324      350606.062
     2407140.907       350656.41     2406984.657      350298.771
#Sta/Elev= 30
       0  463.61    91.9   446.4   155.8  428.51   207.8  405.93   211.8  400.91
   219.8  386.58   223.8  382.11  241.68380.0042  283.09379.0686   295.7  377.02
   375.6  377.02   383.6  378.18   395.6  385.89   415.1   384.1   450.3  376.33
   454.2  376.24   481.5  376.71  513.85383.0678     527383.5915   540.1  384.28
  544.79386.9298     568  390.86   583.9  391.19  623.04 388.545   627.7  388.27
   647.6  396.45   699.4  401.42   743.2  410.33     791  424.55   930.4  471.46
#Mann= 9 ,-1 , 0
       0     .12       0  241.68    .016       0  283.09     .12       0
   450.3    .045       0   481.5     .12       0  513.85     .08       0
     527     .08       0  544.79     .08       0  623.04     .12       0
#XS Ineff= 2 , 0
          396.28  387.36
Permanent Ineff=
       F       F
Bank Sta=450.3,481.5
XS Rating Curve= 0 ,0
Exp/Cntr=0.3,0.1

Type RM Length L Ch R = 1 ,5234.2  ,172.5,233.8,269.1
XS GIS Cut Line= 4
     2407507.715      350919.376     2407290.647       350529.24
      2407155.23      350579.587     2407022.038      350282.658
#Sta/Elev= 30
       0  464.03    87.7   446.9   143.5   430.4   195.3  409.65   203.3  403.03
   211.3  390.54   219.2  382.54   237.1379.4642   278.4379.3885   358.8  377.07
   366.7  379.38   378.7  386.81  396.33387.5841   406.6   390.1  433.83388.8907
   469.9  387.77   477.7  385.19  492.01376.3642   501.1  375.16  522.15376.5854
   551.9   388.9  608.37388.0733   634.6  394.17   666.3  398.36   694.1  409.27
   717.9  407.23   729.8  408.92   801.3   431.5   868.7  456.31   916.4  470.86
#Mann= 8 ,-1 , 0
       0     .12       0   237.1    .016       0   278.4     .12       0
  396.33     .08       0  433.83     .12       0  492.01    .045       0
  522.15     .08       0  608.37     .12       0
#XS Ineff= 2 , 0
          421.05  392.43
Permanent Ineff=
       F       F
Bank Sta=492.01,522.15
XS Rating Curve= 0 ,0
Exp/Cntr=0.3,0.1

Type RM Length L Ch R = 1 ,5000.3  ,274.5,274.6,274.6
XS GIS Cut Line= 4
     2407535.059      350892.033      2407523.34      350677.189
     2407389.225       350346.46     2407240.788      350175.887
#Sta/Elev= 30
       0  459.64    31.9   458.3    39.8  453.97   78.82441.2986   127.5  429.46
   151.4  425.46  161.82425.5447   175.3  425.83   191.3  423.54   223.1  406.52
     235  390.27   242.9  381.85   246.9  380.13  256.91380.9598  296.81378.7426
     354  377.14   357.9  378.32   369.8  386.79   391.8 388.095   413.4   389.4
  431.09387.4913   441.2  385.86     457  375.02     465  374.19   484.8  375.24
   516.5   381.2   544.3  391.12   619.6  409.46   754.5  450.19   798.2  461.39
#Mann= 9 ,-1 , 0
       0     .12       0   78.82     .08       0  161.82     .12       0
  256.91    .016       0  296.81     .12       0   391.8     .08       0
  431.09     .12       0     457    .045       0   484.8     .12       0
#XS Ineff= 2 , 0
          399.59  391.01
Permanent Ineff=
       F       F
Bank Sta=457,484.8
XS Rating Curve= 0 ,0
Exp/Cntr=0.3,0.1

Type RM Length L Ch R = 1 ,4725.7  ,293.7,293.8,293.9
XS GIS Cut Line= 5
     2408001.204       350703.23     2407755.654       350525.15
     2407689.238      350359.882     2407628.572      350208.013
     2407609.277      349964.949
#Sta/Elev= 30
       0  460.18    39.9  453.22    99.8  440.29   139.7   432.9   219.5  412.43
   267.4  398.98   279.4  396.67   295.4   391.9   303.3  391.58   319.1386.6508
  360.62385.4428  410.25385.3156     426  388.88   441.9   388.8  460.09386.7284
   469.6  385.94   473.5  383.85  483.01376.3653   485.4  374.77   489.4  373.76
   497.4  373.03   513.4  376.18   585.2  375.96   601.1   376.2   609.1  377.41
     677   400.1   716.9  414.98   792.9  441.14   828.8  450.74   888.8  469.01
#Mann= 7 ,-1 , 0
       0     .12       0   319.1    .016       0  360.62     .12       0
  410.25     .08       0  460.09     .12       0  483.01    .045       0
   513.4     .12       0
Bank Sta=483.01,513.4
XS Rating Curve= 0 ,0
Exp/Cntr=0.3,0.1

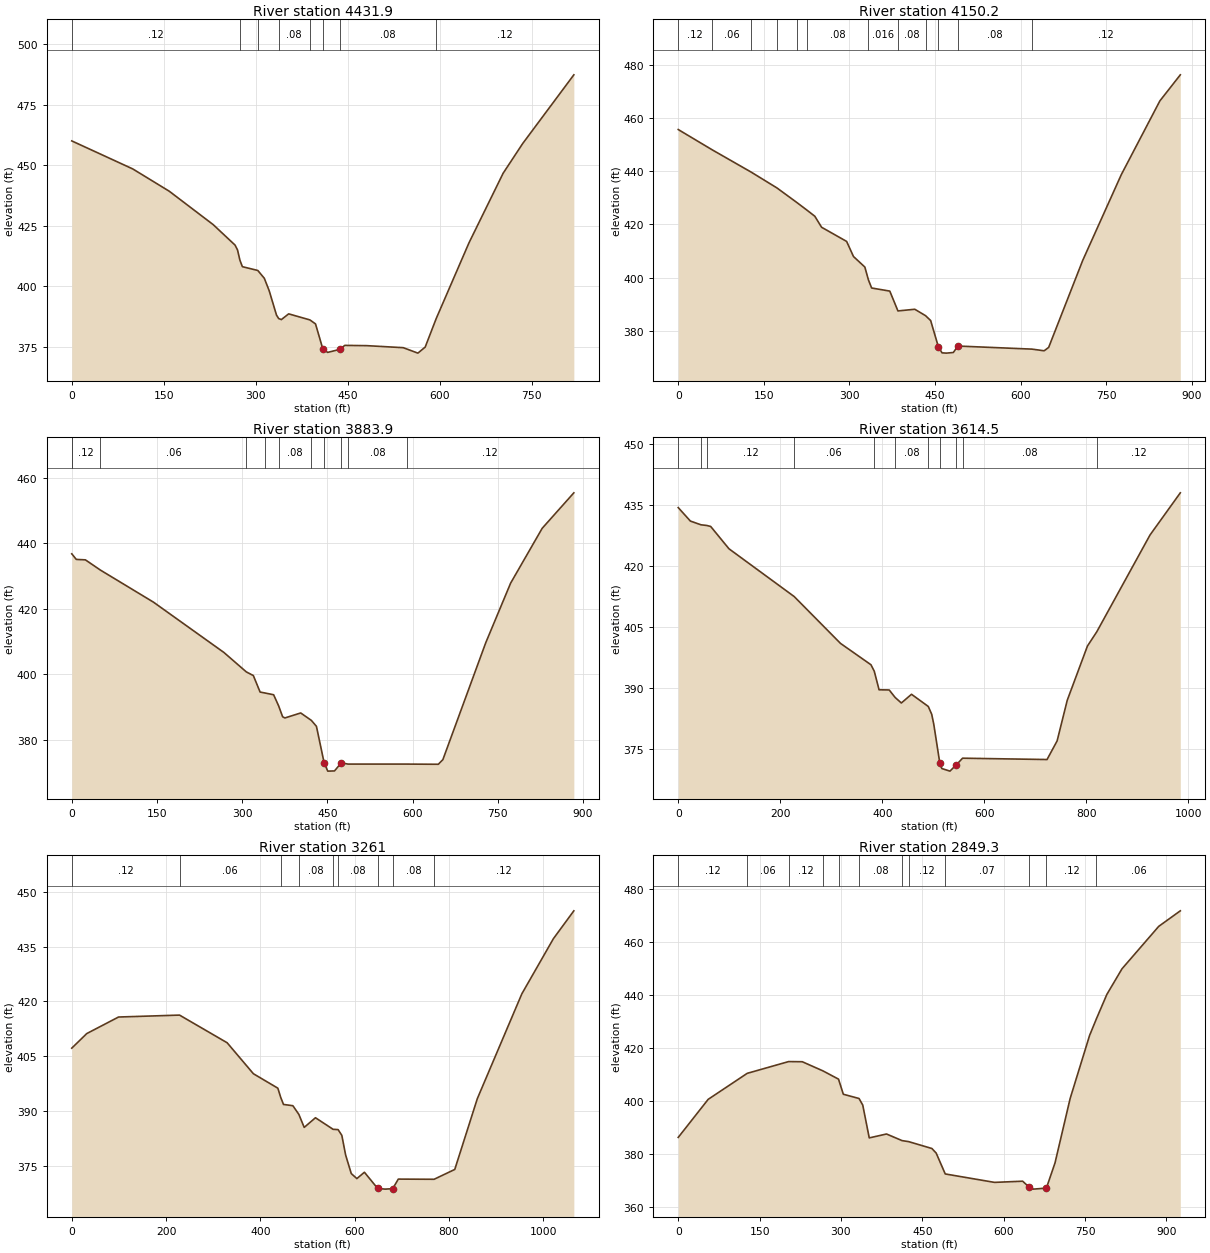
Type RM Length L Ch R = 1 ,4431.9  ,281.7,281.7,281.4
XS GIS Cut Line= 3
     2408114.508      350636.071     2407963.724      350255.342
      2407812.94      349874.613
#Sta/Elev= 30
       0  460.02    99.4  448.45     159  439.23   230.6  425.44   266.4  416.95
   270.4  414.94  274.28410.7217   278.3  408.04  303.46406.4749   314.1  403.24
     322  398.13     334     388  337.55386.5982   341.9  386.17   353.8  388.54
  388.43386.0371   397.6  384.39   409.5  374.08   417.4  372.61   437.3  373.86
   445.3  375.51   481.1   375.4   540.7  374.56   564.6  372.31   576.5   374.8
  594.57386.6445     648  417.92   703.7  446.67   735.5  458.91     819  487.33
#Mann= 8 ,-1 , 0
       0     .12       0  274.28    .016       0  303.46     .12       0
  337.55     .08       0  388.43     .12       0   409.5    .045       0
   437.3     .08       0  594.57     .12       0
Bank Sta=409.5,437.3
XS Rating Curve= 0 ,0
Exp/Cntr=0.3,0.1

Type RM Length L Ch R = 1 ,4150.2  ,266.8,266.3,265.7
XS GIS Cut Line= 4
     2408247.298      350599.064     2408273.998      350273.278
      2408220.47      350140.528     2408067.331      349760.741
#Sta/Elev= 30
       0  455.63   59.63 447.994  127.35439.6969  172.79433.7219  207.83428.2231
  225.42425.3715   239.2  423.09   251.1  418.94     295  413.62     307  407.95
   326.9     404  333.16 399.173   338.8  396.13   370.6  394.97  384.84387.5212
   414.4  388.15  433.29385.7336   442.2  383.91  455.64374.0975   462.1  371.78
     470  371.68   481.9  371.92   489.9  374.34  619.71373.1801     641  372.56
   648.9  373.83   708.6  406.52   776.1  438.68   843.7  466.38   879.5  476.17
#Mann= 12 ,-1 , 0
       0     .12       0   59.63     .06       0  127.35     .08       0
  172.79     .06       0  207.83     .12       0  225.42     .08       0
  333.16    .016       0  384.84     .08       0  433.29     .12       0
  455.64    .045       0   489.9     .08       0  619.71     .12       0
Bank Sta=455.64,489.9
XS Rating Curve= 0 ,0
Exp/Cntr=0.3,0.1

Type RM Length L Ch R = 1 ,3883.9  ,270,269.4,269.1
XS GIS Cut Line= 4
     2408553.288      350494.897     2408523.748      350172.543
     2408463.931      350034.142     2408301.468      349658.248
#Sta/Elev= 30
       0  436.76     .32436.6984       8  435.05      24  434.92   50.52431.7906
   143.9  422.02   267.8   406.7  307.36400.7625   319.7  399.65   331.6  394.62
  340.68394.3183   355.4   393.8  364.14390.4474   371.3  387.08   375.3  386.73
   403.1  388.25   421.9385.9775   430.8  384.17  444.36373.0422   450.7  370.52
   462.6  370.58   474.5  373.04  486.49372.6675  589.53372.6626   645.4  372.61
   653.4  374.02   728.9  409.66   772.7  427.82   828.3  444.54     884  455.35
#Mann= 11 ,-1 , 0
       0     .06       0     .32     .12       0   50.52     .06       0
  307.36     .08       0  340.68    .016       0  364.14     .08       0
   421.9     .12       0  444.36    .045       0   474.5     .12       0
  486.49     .08       0  589.53     .12       0
Bank Sta=444.36,474.5
XS Rating Curve= 0 ,0
Exp/Cntr=0.3,0.1

Type RM Length L Ch R = 1 ,3614.5  ,349.1,353.4,357.2
XS GIS Cut Line= 4
       2408748.6      350468.855     2408752.506      350019.637
     2408619.944      349727.145     2408445.215      349604.272
#Sta/Elev= 30
       0  434.39    23.8  431.08   44.61430.1609   55.79429.9975    63.6  429.75
    99.4  424.27  227.28412.5218     318  401.01   377.7  395.76  384.24394.1566
   393.6  389.61   413.5  389.56  425.12387.7119   437.3  386.36   457.2   388.5
  490.07 385.508   496.8  383.58   500.8  381.15   512.7  371.55   516.6  370.25
   532.5  369.61   544.4  371.08   557.3  372.79   722.8  372.46   742.6  377.05
   762.4  387.02     802  400.36  820.33403.8693   924.6  427.65     984  438.02
#Mann= 11 ,-1 , 0
       0     .12       0   44.61     .06       0   55.79     .12       0
  227.28     .06       0  384.24    .016       0  425.12     .08       0
  490.07     .12       0   512.7    .045       0   544.4     .12       0
   557.3     .08       0  820.33     .12       0
Bank Sta=512.7,544.4
XS Rating Curve= 0 ,0
Exp/Cntr=0.3,0.1

Type RM Length L Ch R = 1 ,3261    ,413.3,411.7,426.6
XS GIS Cut Line= 4
     2409406.152      350229.272     2409080.631      350023.543
     2408943.913      349576.928     2408979.069      349367.293
#Sta/Elev= 30
       0   407.2    31.8   411.2    99.2  415.74  228.53416.2664   329.5  408.68
   385.1  400.19     437  396.22  443.11393.6884     449  391.76   468.9  391.41
  481.57389.0303   492.9  385.46   516.8  388.11  554.17  384.94  564.73 384.857
   572.7  383.28   580.7  377.91   592.7   372.8   604.6  371.42   620.6  373.16
   648.6  368.73   664.5  368.53   680.5  368.65   692.5  371.28  768.38371.2308
   812.2  373.93     860  393.34   954.5  422.12  1021.4  437.24  1064.7  444.87
#Mann= 9 ,-1 , 0
       0     .12       0  228.53     .06       0  443.11    .016       0
  481.57     .08       0  554.17     .12       0  564.73     .08       0
   648.6    .045       0   680.5     .08       0  768.38     .12       0
Bank Sta=648.6,680.5
XS Rating Curve= 0 ,0
Exp/Cntr=0.3,0.1

Type RM Length L Ch R = 1 ,2849.3  ,282.7,283.1,283.4
XS GIS Cut Line= 3
     2409567.611       350078.23     2409412.663      349932.397
     2409201.725      349251.408
#Sta/Elev= 30
       0  386.29    55.2  400.63   127.2410.4356   203.5414.8644   228.7  414.81
  266.87 411.357  295.54408.2457   304.4  402.55  333.37400.9531   340.2  398.47
   352.2   386.1     384  387.57  412.71385.0757  424.76384.6969   467.7   382.1
   475.6  380.37  492.29372.5117   583.2  369.33     635  369.78   646.9  367.56
   654.9  366.79   678.8  367.18   694.7  376.68   722.6  400.96   758.4   424.7
  770.98430.9733   790.3  440.19   818.2  449.84   885.9  465.83   925.7  471.69
#Mann= 12 ,-1 , 0
       0     .12       0   127.2     .06       0   203.5     .12       0
  266.87     .06       0  295.54    .016       0  333.37     .08       0
  412.71     .06       0  424.76     .12       0  492.29     .07       0
   646.9    .045       0   678.8     .12       0  770.98     .06       0
Bank Sta=646.9,678.8
XS Rating Curve= 0 ,0
Exp/Cntr=0.3,0.1

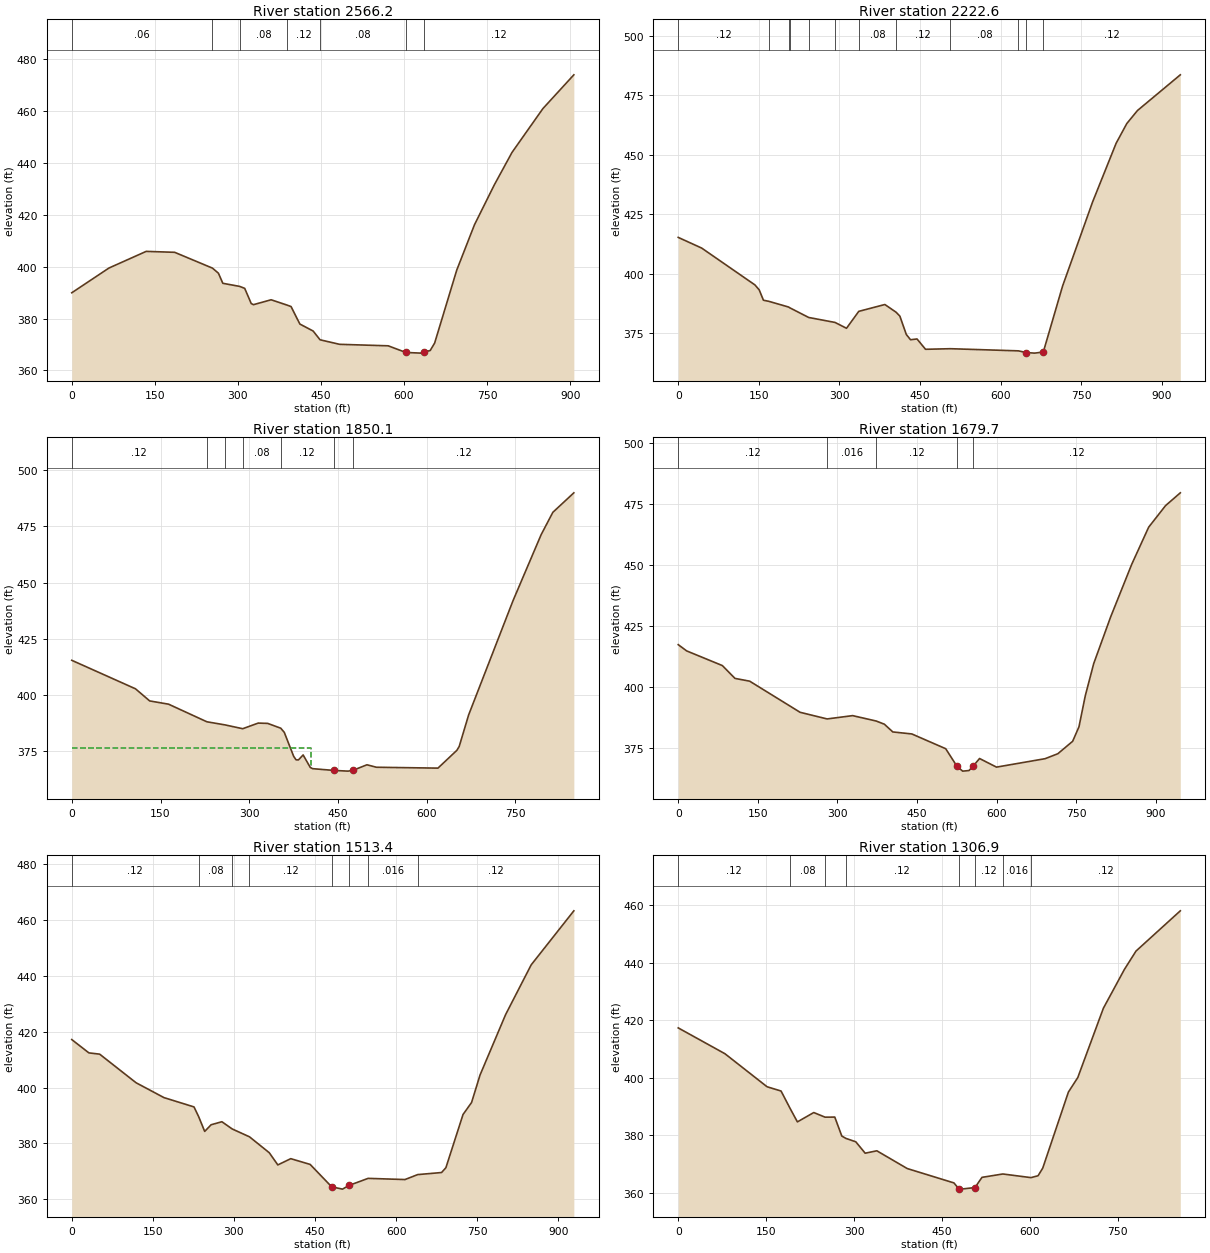
Type RM Length L Ch R = 1 ,2566.2  ,342.9,343.6,344.2
XS GIS Cut Line= 3
     2409587.142      350037.866     2409627.506      349716.251
     2409462.142      349157.658
#Sta/Elev= 30
       0  389.94    67.2   399.5   134.4  405.92   185.8  405.56  254.04399.4587
   264.8  397.51   272.8   393.6  303.21392.4039   312.3  391.65   324.1  385.78
   328.1  385.35     360  387.24     389  385.17     396  384.63   411.9  377.88
   435.9  375.18  448.37   371.8   483.7  370.05   571.5  369.47   603.4   366.9
   631.4  366.65   635.4  366.96   647.3  367.66   655.3  370.53   695.2  398.67
   727.1  416.12     763  431.56     795   444.1   850.8  461.02   906.7  474.06
#Mann= 7 ,-1 , 0
       0     .06       0  254.04    .016       0  303.21     .08       0
     389     .12       0  448.37     .08       0   603.4    .045       0
   635.4     .12       0
Bank Sta=603.4,635.4
XS Rating Curve= 0 ,0
Exp/Cntr=0.3,0.1

Type RM Length L Ch R = 1 ,2222.6  ,373.2,372.5,371
XS GIS Cut Line= 3
     2410124.902      349920.678     2409910.059      349601.668
     2409768.131      349070.418
#Sta/Elev= 30
       0  415.21    43.6  410.73   142.7  395.26   150.7  393.18   158.6  388.82
  168.68388.3564  205.28385.9688   207.6385.6475  242.79 381.577  291.88379.4894
   313.2  377.04  336.02384.1448   384.6  387.02  405.38383.8028   412.5  382.15
   424.5  374.44   432.4  372.21   444.4  372.56   460.3  368.21  506.74368.4544
  633.16367.5525   647.6  366.84   663.5   366.6   679.5  367.07   715.3  394.72
   771.1  430.02     815  454.73   834.9  463.03   854.8  468.51   934.5   483.5
#Mann= 12 ,-1 , 0
       0     .12       0  168.68    .016       0  205.28     .12       0
   207.6     .08       0  242.79    .016       0  291.88     .12       0
  336.02     .08       0  405.38     .12       0  506.74     .08       0
  633.16     .12       0   647.6    .045       0   679.5     .12       0
Bank Sta=647.6,679.5
XS Rating Curve= 0 ,0
Exp/Cntr=0.3,0.1

Type RM Length L Ch R = 1 ,1850.1  ,154.9,170.4,187.2
XS GIS Cut Line= 4
     2410368.913      349810.349     2410169.694      349540.817
     2410090.267      349202.276     2410078.548      349036.911
#Sta/Elev= 30
       0  415.28   107.7  402.56   131.7  397.15   163.6   395.7  228.36387.8416
  258.65386.4706  289.01384.7487   315.2  387.26   331.2  387.12  353.28384.9772
   359.2  383.14   375.1  372.42   379.1  370.88   383.1  370.81   391.1  373.04
   403.1   367.5   407.1  366.92   443.1  366.13   467.1  365.82   475.3  366.18
     499  368.65     515  367.55     619  367.16   650.9  375.08   654.9  376.82
   670.9  390.93     746  441.96   793.4  471.33   813.2  481.32   848.7  490.02
#Mann= 7 ,-1 , 0
       0     .12       0  228.36     .08       0  258.65    .016       0
  289.01     .08       0  353.28     .12       0   443.1    .045       0
   475.3     .12       0
#XS Ineff= 2 , 0
          404.54  376.08
Permanent Ineff=
       F       F
Bank Sta=443.1,475.3
XS Rating Curve= 0 ,0
Exp/Cntr=0.3,0.1

Type RM Length L Ch R = 1 ,1679.7  ,165.5,166.2,168.2
XS GIS Cut Line= 4
     2410409.277      349803.838     2410211.361      349531.703
     2410371.517      349158.005     2410272.559      348980.921
#Sta/Elev= 30
       0  417.21    15.8  414.65    83.1  408.64   106.9  403.38   134.6  402.24
   229.6  389.48  280.54386.7596   328.6  388.12  372.97 385.903   388.3  384.61
   404.3  381.43   440.1  380.61   503.9  374.56     525 367.408   535.8  365.37
   547.8   365.6     555367.2677   567.7  370.54   599.6  367.01   691.2  370.47
   715.2  372.51   743.1   377.6     755  383.56   766.9  396.28   782.8  409.49
   814.7   428.6   854.4  450.16   886.3  465.36   918.1  474.19   945.9  479.44
#Mann= 5 ,-1 , 0
       0     .12       0  280.54    .016       0  372.97     .12       0
     525    .045       0     555     .12       0
Bank Sta=525,555
XS Rating Curve= 0 ,0
Exp/Cntr=0.3,0.1

Type RM Length L Ch R = 1 ,1513.4  ,217.4,206.5,193
XS GIS Cut Line= 4
     2410440.527      349785.609     2410381.934      349493.942
      2410542.09      349120.244     2410496.517      348900.192
#Sta/Elev= 30
       0  417.18    31.7  412.41    51.6  411.96     119  401.71   170.6  396.39
   226.1  393.06  234.59389.6421   245.9  384.28   257.8  386.67   277.7  387.75
  296.85385.1575  328.72382.3533   365.3  376.66   381.2  372.28   405.1  374.52
     441  372.46   480.8  364.44   500.8  363.61   512.7  364.92  548.21367.4641
   616.4  367.04  639.87368.8114   684.1  369.56   692.1  371.28   723.8  390.34
   739.6  394.64   755.3   404.5   802.6  426.14   849.9  443.95   928.8   463.3
#Mann= 8 ,-1 , 0
       0     .12       0  234.59     .08       0  296.85    .016       0
  328.72     .12       0   480.8    .045       0   512.7     .12       0
  548.21    .016       0  639.87     .12       0
Bank Sta=480.8,512.7
XS Rating Curve= 0 ,0
Exp/Cntr=0.3,0.1

Type RM Length L Ch R = 1 ,1306.9  ,205.2,206,206.4
XS GIS Cut Line= 3
     2410648.861      349730.921     2410626.725      349081.182
     2410581.152      348879.359
#Sta/Elev= 30
       0  417.37    79.8  408.37   151.6  396.89   175.5   395.4  191.08389.2978
   203.4  384.66   231.3  387.91  250.69386.3037   267.2  386.33   279.2  379.74
  286.16378.9152   303.1  377.73   319.1  373.76     339   374.6   390.9  368.42
   470.6  363.42   478.6  361.47   482.6  361.26   506.5  361.81   518.5  365.36
  554.08366.5272  602.14 365.264   614.2  365.92   622.2  368.58     666  395.04
     682  400.09   725.7  424.22   761.5  437.69   781.4  444.11     857  458.11
#Mann= 8 ,-1 , 0
       0     .12       0  191.08     .08       0  250.69    .016       0
  286.16     .12       0   478.6    .045       0   506.5     .12       0
  554.08    .016       0  602.14     .12       0
Bank Sta=478.6,506.5
XS Rating Curve= 0 ,0
Exp/Cntr=0.3,0.1

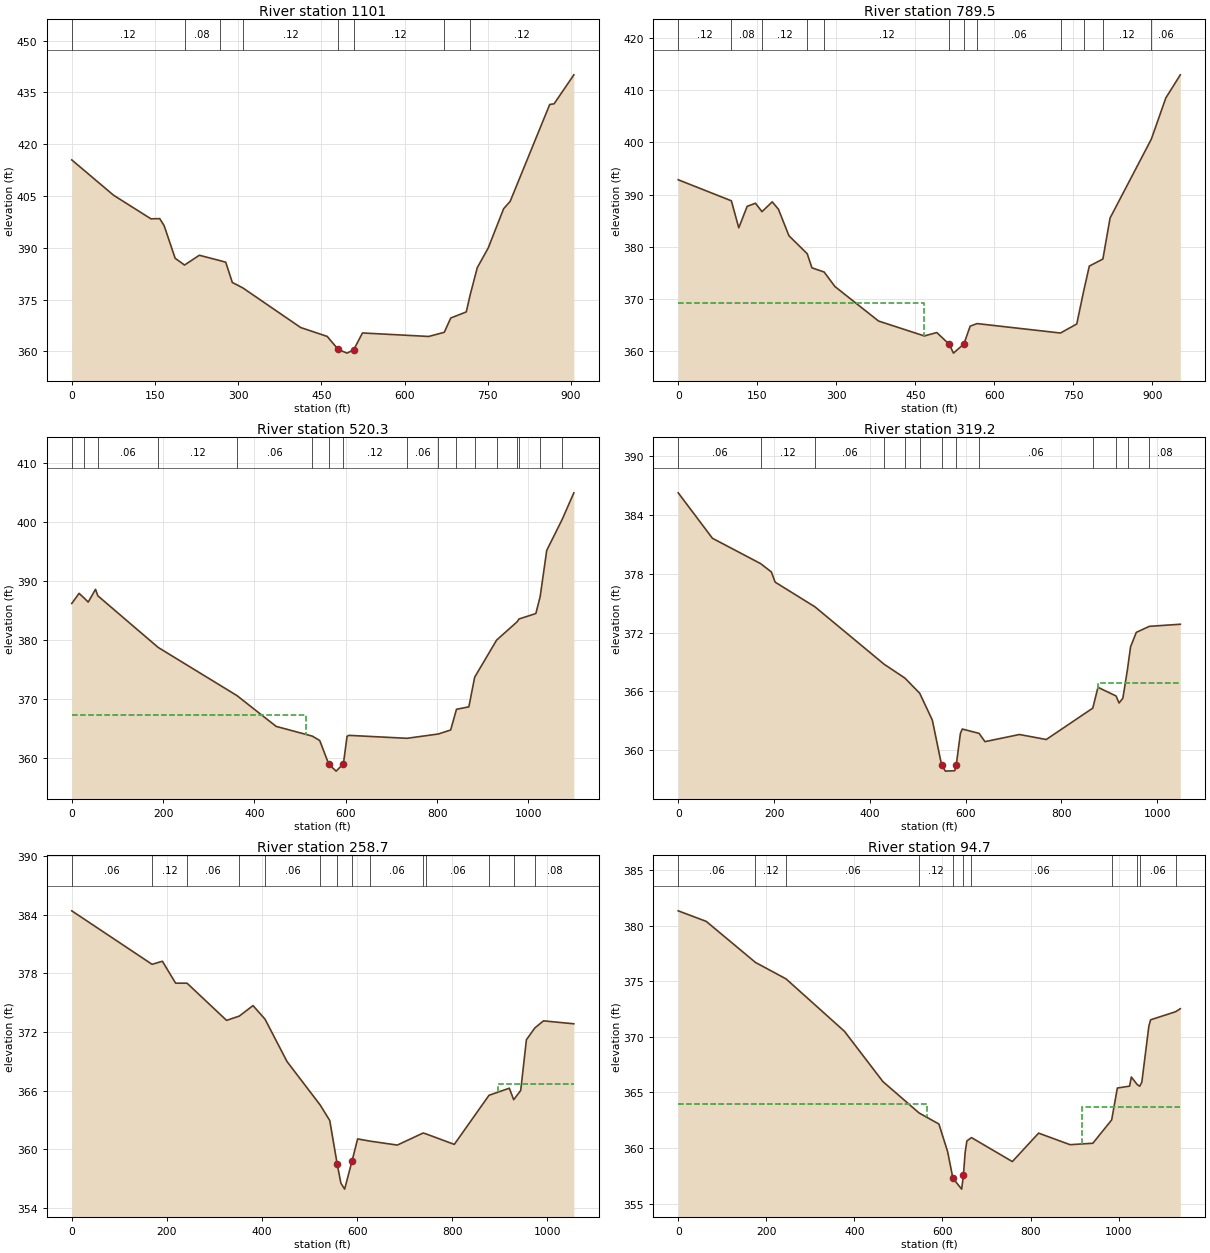
Type RM Length L Ch R = 1 ,1101    ,314.8,311.4,305.8
XS GIS Cut Line= 4
     2410777.767      349730.921     2410838.965       349423.63
     2410834.226      349009.767     2410759.538      348848.109
#Sta/Elev= 30
       0  415.46    75.4  405.22   142.8  398.39   158.6  398.45   166.6  396.39
   186.4  386.97  203.31 385.006     230  387.84  266.71386.3075   277.6  385.82
   289.5  379.96  308.44378.3824   412.8   366.9   460.6  364.33   480.5  360.55
   496.4  359.49   508.3  360.46   524.2  365.33   643.6  364.32  671.62 365.519
   683.4  369.67   711.3  371.42  718.36376.3622   731.2  384.25     751  389.98
   778.7  401.32   790.5  403.45   861.8  431.51   869.7   431.7   905.3   440.1
#Mann= 8 ,-1 , 0
       0     .12       0  203.31     .08       0  266.71    .016       0
  308.44     .12       0   480.5    .045       0   508.3     .12       0
  671.62    .016       0  718.36     .12       0
Bank Sta=480.5,508.3
XS Rating Curve= 0 ,0
Exp/Cntr=0.3,0.1

Type RM Length L Ch R = 1 ,789.5   ,275.5,269.3,265
XS GIS Cut Line= 5
     2411091.569      349686.651     2411166.498      349398.979
      2411132.46      349172.534     2411069.386      348910.307
     2410967.871      348790.817
#Sta/Elev= 30
       0  392.84  100.83388.8009   114.9  383.61   130.8  387.74   146.6  388.33
  158.94386.7145   178.4   388.6   190.2  387.17   210.1  382.09  244.84378.6273
   253.7  375.93  276.93375.1253   297.3  372.34   380.2  365.71     467  362.85
   490.7   363.5   514.4  361.24   522.3  359.55   542.1  361.31     554  364.73
  567.19365.2223  725.44363.4105   756.3  365.15  769.53371.5216   780.1  376.26
  805.86377.6147   819.5  385.49  897.84400.6488   925.3  408.55   952.8  412.99
#Mann= 12 ,-1 , 0
       0     .12       0  100.83     .08       0  158.94     .12       0
  244.84     .06       0  276.93     .12       0   514.4    .045       0
   542.1     .12       0  567.19     .06       0  725.44     .12       0
  769.53    .016       0  805.86     .12       0  897.84     .06       0
#XS Ineff= 2 , 0
          466.46  369.16
Permanent Ineff=
       F       F
Bank Sta=514.4,542.1
XS Rating Curve= 0 ,0
Exp/Cntr=0.3,0.1

Type RM Length L Ch R = 1 ,520.3   ,182.4,201.1,210.4
XS GIS Cut Line= 4
     2411393.652      349634.567     2411436.621      349249.151
     2411230.892      348769.984     2411043.392      348738.734
#Sta/Elev= 30
       0  386.16      16  387.88   27.33387.0656      36   386.4      52  388.56
   57.09 387.463  189.14378.7211  361.61370.5628   447.5  365.34  526.68363.6908
     543  362.94     563  358.89   578.9  357.76   594.8  359.01   602.8  363.66
   606.7  363.82  734.12363.3205  802.78364.0524   829.7  364.73  842.39368.2367
   869.5  368.65  882.24373.6688  930.21379.9542  975.25383.0648  979.36383.5374
  1016.2  384.46 1025.69387.3426    1040  395.15 1073.69400.3771  1099.4  404.91
#Mann= 17 ,-1 , 0
       0     .08       0   27.33     .12       0   57.09     .06       0
  189.14     .12       0  361.61     .06       0  526.68     .12       0
     563    .045       0   594.8     .12       0  734.12     .06       0
  802.78     .12       0  842.39    .016       0  882.24     .12       0
  930.21     .08       0  975.25     .12       0  979.36     .08       0
 1025.69     .12       0 1073.69     .06       0
#XS Ineff= 2 , 0
          513.93  367.33
Permanent Ineff=
       F       F
Bank Sta=563,594.8
XS Rating Curve= 0 ,0
Exp/Cntr=0.3,0.1

Type RM Length L Ch R = 1 ,319.2   ,70.8,60.4,59.2
XS GIS Cut Line= 4
      2411479.59      349575.974     2411543.392      349128.057
     2411540.788      348963.994     2411365.006      348569.463
#Sta/Elev= 30
       0  386.28    71.4  381.64  172.08379.0494   194.5   378.2   202.4  377.16
  285.58374.6354  430.07368.7712  473.33 367.362   504.2365.8149   530.6  363.07
   550.1  358.45   557.9  357.86   577.4   357.9   580.6  358.51   589.2  361.71
   593.1  362.16  628.26361.7142   640.5  360.87   712.5   361.6   768.5  361.09
  865.58 364.292   876.5  366.42  914.28365.5341   920.5  364.82   928.5  365.31
  938.17368.2847   944.5  370.55   956.5  372.03  983.75372.6465  1048.4  372.86
#Mann= 13 ,-1 , 0
       0     .06       0  172.08     .12       0  285.58     .06       0
  430.07     .08       0  473.33     .06       0   504.2     .12       0
   550.1    .045       0   580.6     .12       0  628.26     .06       0
  865.58    .016       0  914.28     .06       0  938.17     .12       0
  983.75     .08       0
#XS Ineff= 2 , 0
                          875.54          366.88
Permanent Ineff=
       F       F
Bank Sta=550.1,580.6
XS Rating Curve= 0 ,0
Exp/Cntr=0.3,0.1

Type RM Length L Ch R = 1 ,258.7   ,166.2,164,162.1
XS GIS Cut Line= 4
     2411536.881      349559.046     2411600.684       349111.13
     2411598.079      348947.067     2411419.694      348546.026
#Sta/Elev= 30
       0  384.38  168.85378.9146   190.5  379.23   218.3  376.99  242.31376.9879
   325.4  373.19  352.18 373.628     381   374.7  406.24373.3128   452.4  368.99
  522.23364.5399   542.3  362.96   557.9  358.53   565.7  356.56   573.6  355.95
   589.2  358.84   600.9  361.08  626.59360.8561   684.4  360.45  738.55361.6818
  743.98361.6049   804.1  360.52  877.07365.5368   919.8  366.26  928.91365.0845
   943.7  366.03   955.7  371.21  973.49372.4203   991.6  373.14  1055.4  372.84
#Mann= 14 ,-1 , 0
       0     .06       0  168.85     .12       0  242.31     .06       0
  352.18     .08       0  406.24     .06       0  522.23     .12       0
   557.9    .045       0   589.2     .12       0  626.59     .06       0
  738.55     .08       0  743.98     .06       0  877.07    .016       0
  928.91     .12       0  973.49     .08       0
#XS Ineff= 2 , 0
                          895.36          366.71
Permanent Ineff=
       F       F
Bank Sta=557.9,589.2
XS Rating Curve= 0 ,0
Exp/Cntr=0.3,0.1

Type RM Length L Ch R = 1 ,94.7    ,87.6,94.7,101.5
XS GIS Cut Line= 4
     2411625.335      349546.559     2411764.311      349102.983
     2411709.276      348581.498     2411601.637      348475.595
#Sta/Elev= 30
       0  381.35    63.6   380.4  175.35376.7062  244.92375.2224   377.4  370.51
   464.8  365.98  546.85 363.159     592  362.16   611.8  359.67   623.7  357.29
   643.6   356.3   647.6  357.53   651.6  359.61   655.5  360.64  665.98360.9373
   758.8  358.78   818.4  361.34   889.9   360.3   941.6  360.43  984.34362.5321
   997.2   365.4    1025  365.57    1029  366.39 1042.32365.7145 1047.93365.5609
  1052.8  365.92  1068.7  370.95  1072.7  371.54 1129.61372.2695  1140.2  372.54
#Mann= 11 ,-1 , 0
       0     .06       0  175.35     .12       0  244.92     .06       0
  546.85     .12       0   623.7    .045       0   647.6     .12       0
  665.98     .06       0  984.34    .016       0 1042.32     .08       0
 1047.93     .06       0 1129.61     .08       0
#XS Ineff= 2 , 0
          564.71  363.97  916.41          363.67
Permanent Ineff=
       F       F
Bank Sta=623.7,647.6
XS Rating Curve= 0 ,0
Exp/Cntr=0.3,0.1
LCMann Table=0

Chan Stop Cuts=-1
Use User Specified Reach Order=0
Composite Channel Slope=5